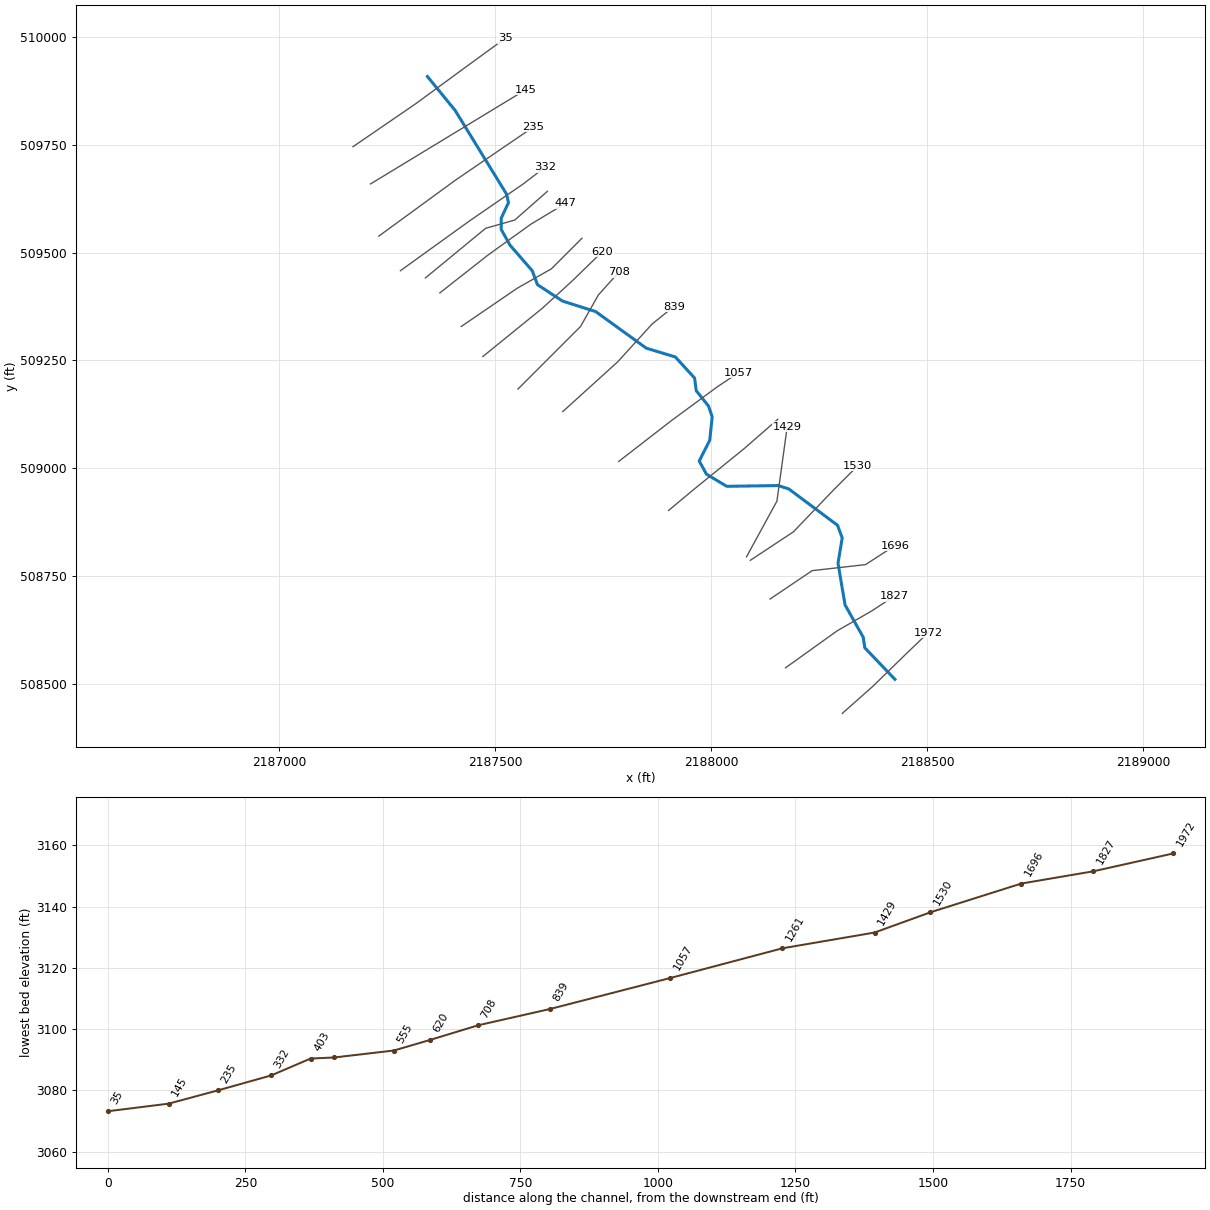
--- SFGAULYRV.prj (project) ---

Proj Title=SFGAULYRV
Current Plan=p01
Default Exp/Contr=0,0
English Units
Geom File=g01
Flow File=f01
Plan File=p01
Background Map Layer=Inundation Boundary (01pct Value_0)
Background Map Layer=Inundation Boundary (10pct Value_0)
BEGIN DESCRIPTION:
----------MODEL BY WOOD PLC 2021----------
Stream Name: South Fork Gauley River
Flood Zone: Approximate
Pocahontas County, WV
HEC-RAS Version: RAS 6.1
Vertical Datum: NAVD88
Projection: NAD 1983 StatePlane West Virginia S FIPS 4702 (US Feet)
Terrain: 1-meter LIDAR (FEMA Region III 3DEP collected 2016-2018)
Land Use: 2019 NLCD
Hydrologic Method:
WV 2010 Regional Regression Equations
Model Notes:
Model extends beyond county boundary on the downstream end
END DESCRIPTION:
DSS Export Rating Curves= 0
DSS Export Rating Curve Sorted= 0
DSS Export Volume Flow Curves= 0
DXF OffsetX= 0
DXF OffsetY= 0
DXF ScaleX= 0
DXF ScaleY= 0

--- SFGAULYRV.p01 (plan) ---

Plan Title=Floodplain
Program Version=6.10
Short Identifier=Floodplain
Geom File=g01
Flow File=f01
Subcritical Flow
K Sum by GR= 0
Std Step Tol= 0.01
Critical Tol= 0.01
Num of Std Step Trials= 20
Max Error Tol= 0.3
Flow Tol Ratio= 0.001
Split Flow NTrial= 30
Split Flow Tol= 0.02
Split Flow Ratio= 0.02
Log Output Level= 0
Friction Slope Method= 1
Unsteady Friction Slope Method= 2
Unsteady Bridges Friction Slope Method= 1
Parabolic Critical Depth
Global Vel Dist= 0 , 0 , 0
Global Log Level= 0
CheckData=True
Encroach Param=-1 ,0,0, 0
Mapping Interval=1HOUR
Computation Time Step Use Courant=        0
Computation Time Step Use Time Series=    0
Computation Time Step Count To Double=0
Computation Time Step Max Doubling=0
Computation Time Step Max Halving=0
Computation Time Step Residence Courant=0
Run HTab= 0
Run UNet= 0
Run Sediment= 0
Run PostProcess= 0
Run WQNet= 0
Run RASMapper=-1
UNET Theta= 0
UNET Theta Warmup= 0
UNET ZTol= 0
UNET ZSATol= 0
UNET MxIter= 0
UNET Max Iter WO Improvement= 0
UNET MaxInSteps= 0
UNET DtIC= 0
UNET DtMin= 0
UNET MaxCRTS= 0
UNET WFStab= 0
UNET SFStab= 0
UNET WFX= 1
UNET SFX= 1
UNET Gravity=32.174
UNET 1D Methodology=Finite Difference
UNET DSS MLevel= 1
UNET Pardiso=0
UNET DZMax Abort= 0
UNET Use Existing IB Tables= 0
UNET Froude Reduction=False
UNET Froude Limit= 0
UNET Froude Power= 0
UNET D1 Cores= 0
UNET WindReference=Eulerian
UNET WindDragFormulation=Hsu (1988)
UNET D2 Coriolis=0
UNET D2 Cores= 0
UNET D2 Theta= 1
UNET D2 Theta Warmup= 1
UNET D2 Z Tol= 0.01
UNET D2 Volume Tol= 0.01
UNET D2 Max Iterations= 20
UNET D2 Equation= 0
UNET D2 RampUpFraction=0.1
UNET D2 TimeSlices= 1
UNET D2 Turbulence Formulation=Non-Conservative (original)
UNET D2 Eddy Viscosity=0.3
UNET D2 Transverse Eddy Viscosity=0.1
UNET D2 Smagorinsky Mixing=0
UNET D2 BCVolumeCheck=0
UNET D2 Cores=0
UNET D2 SolverType=PARDISO (Direct)
UNET D2 Minimum Iterations= 2147483647
UNET D2 Maximum Iterations= 2147483647
UNET D2 Restart Number= 10
UNET D2 Relaxation Coeff=1.3
UNET D2 SOR Precondition Iterations= 10
UNET D2 ILUT Maximum Fill= 8
UNET D2 ILUT Tolerance=1E-08
UNET D1D2 MaxIter= 0
UNET D1D2 ZTol=0.01
UNET D1D2 QTol=0.1
UNET D1D2 MinQTol=1
Write IC File= 0
Write IC File at Fixed DateTime=0
Write IC File at Sim End=0
Echo Input=False
Echo Parameters=False
Echo Output=False
Write Detailed= 0
HDF Write Warmup=0
HDF Write Time Slices=0
HDF Flush=0
HDF Compression= 1
HDF Chunk Size= 1
HDF Spatial Parts= 1
HDF Use Max Rows=0
HDF Fixed Rows= 1
Calibration Method= 0
Calibration Iterations= 20
Calibration Max Change=0.05
Calibration Tolerance=0.2
Calibration Maximum=1.5
Calibration Minimum=0.5
Calibration Optimization Method= 1
WQ AD Non Conservative
WQ ULTIMATE=-1
WQ Max Comp Step=1HOUR
WQ Output Interval=15MIN
WQ Output Selected Increments= 0
WQ Output face flow=0
WQ Output face velocity=0
WQ Output face area=0
WQ Output face dispersion=0
WQ Output cell volume=0
WQ Output cell surface area=0
WQ Output cell continuity=0
WQ Output cumulative cell continuity=0
WQ Output face conc=0
WQ Output face dconc_dx=0
WQ Output face courant=0
WQ Output face peclet=0
WQ Output face adv mass=0
WQ Output face disp mass=0
WQ Output cell mass=0
WQ Output cell source sink temp=0
WQ Output nsm pathways=0
WQ Output nsm derived pathways=0
WQ Create Restart=0
WQ Fixed Restart=0
WQ System Summary=0
WQ Write To DSS=0
Sorting and Armoring Iterations= 10
XS Update Threshold= 0.02
Bed Roughness Predictor= 0
Hydraulics Update Threshold= 0.02
Energy Slope Method= 1
Volume Change Method= 1
Sediment Retention Method= 0
Sediment TS Multiplier= 1
Warm Up Method= 0
XS Weighting Method= 0
Number of US Weighted Cross Sections= 1
Number of DS Weighted Cross Sections= 1
Upstream XS Weight=0
Main XS Weight=1
Downstream XS Weight=0
Number of DS XS's Weighted with US Boundary= 1
Upstream Boundary Weight= 1
Weight of XSs Associated with US Boundary= 0
Number of US XS's Weighted with DS Boundary= 1
Downstream Boundary Weight= 0.5
Weight of XSs Associated with DS Boundary= 0.5
Percentile Method= 0
Sediment Output Level= 3
Mass or Volume Output= 0
Output Increment Type= 1
Profile and TS Output Increment= 1
Transport Output Increment 1
XS Output Flag= 0
XS Output Increment= 10
Read HDF5 Sediment Hotstart= 0
Sediment Hotstart Type= 0
Write Gradation File= 0
Read Gradation Hotstart= 0
Write HDF5 File= 1
Write Binary Output= 1
Write DSS Sediment File= 0
DSS Sediment Output Type= 1
SV Curve= 0
Specific Gage Flag= 0
Subcell Erosion Methods= 0
Subcell Deposition Methods= 0
Advection Scheme= 1
Matrix Solver= 0
Implicit Weighting Factor= 1
Maximum Outer Loop Convergence Iterations= 5
Convergence Maximum Absolute= 0.001
Convergence RMSE= 0.0001
Grain Fractions Max Abs Error= 0.001
Max Subgrid Regions= 1
Max Subgrid Length Scale= 3.402823E+38
Initial Layer Thickness= 3.402823E+38
Min Layer Thickness= 3.402823E+38
Max Layer Thickness= 3.402823E+38
Number of Layers= 5

--- SFGAULYRV.f01 (steady flow) ---

Flow Title=Flow
Program Version=6.10
Number of Profiles= 6
Profile Names=01pct,10pct,04pct,02pct,0_2pct,01plus
River Rch & RM=SFGAULYRV,Main            ,1972
     539     284     378     456     754     798
River Rch & RM=SFGAULYRV,Main            ,1057
     729     389     514     618    1010    1080
Boundary for River Rch & Prof#=SFGAULYRV,Main            , 1
Up Type= 0
Dn Type= 1
Dn Known WS=3075.7
Boundary for River Rch & Prof#=SFGAULYRV,Main            , 2
Up Type= 0
Dn Type= 1
Dn Known WS=3074.9
Boundary for River Rch & Prof#=SFGAULYRV,Main            , 3
Up Type= 0
Dn Type= 1
Dn Known WS=3075.2
Boundary for River Rch & Prof#=SFGAULYRV,Main            , 4
Up Type= 0
Dn Type= 1
Dn Known WS=3075.4
Boundary for River Rch & Prof#=SFGAULYRV,Main            , 5
Up Type= 0
Dn Type= 1
Dn Known WS=3076.2
Boundary for River Rch & Prof#=SFGAULYRV,Main            , 6
Up Type= 0
Dn Type= 1
Dn Known WS=3076.3
DSS Import GetInterval= 0
DSS Import GetPeak= 0
DSS Import FillOption= 0

--- SFGAULYRV.g01 (geometry) ---

Geom Title=Geometry
Program Version=6.10

River Reach=SFGAULYRV       ,Main
Reach XY= 30
     2188425.632      508511.853     2188355.935      508584.801
     2188352.175      508609.277      2188310.12      508684.327
     2188293.851      508780.812     2188303.592      508839.285
     2188292.708      508868.581     2188179.852      508952.672
     2188155.602      508960.437     2188036.258      508958.718
      2187989.23      508986.892     2187972.566      509017.364
     2187996.914      509065.336     2188002.575      509119.648
      2187994.09       509144.49     2187965.595      509180.164
     2187961.853      509209.392     2187917.129      509258.239
     2187850.141      509278.4672187732.81863664509363.248594163
     2187656.024      509387.6382187598.08656321509425.497435713
2187585.99550375509457.770990494     2187534.518      509516.988
2187514.19853889509553.1907017092187514.19853889509579.605297761
2187531.04922948509615.5837992812187526.48936626509635.183901844
     2187407.395      509829.088     2187343.362      509907.382

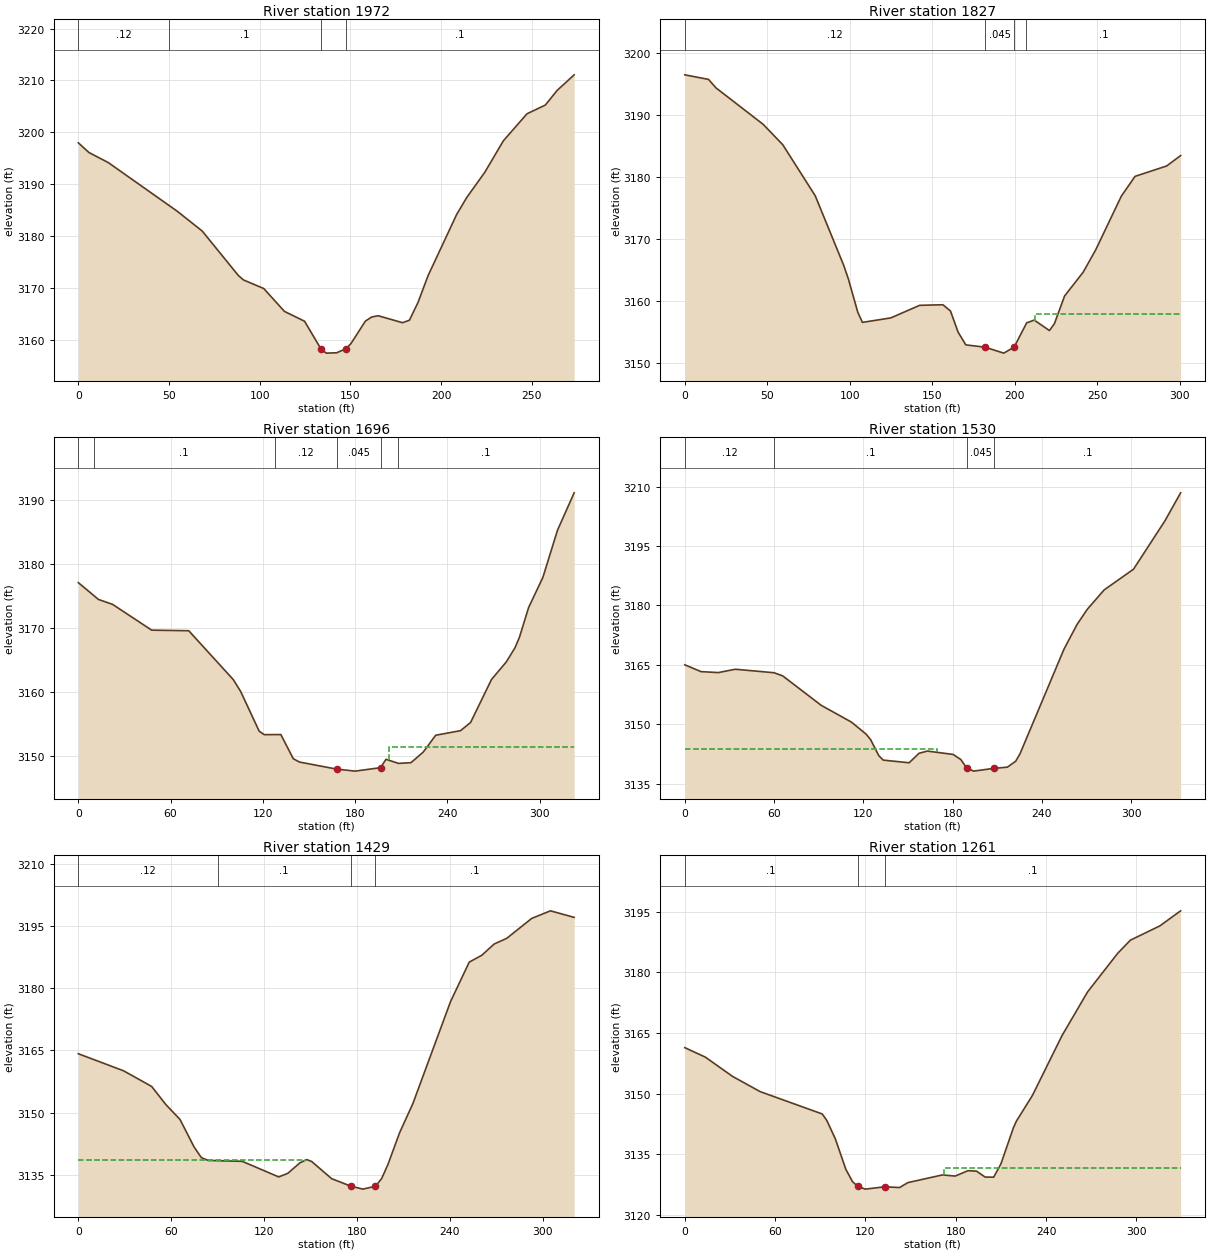
Type RM Length L Ch R = 1 ,1972    ,148,145.7,141.7
XS GIS Cut Line= 4
2188303.83112464 508433.066739412188373.50803619508494.780575359
2188451.14802335508570.4297936192188502.90801479508620.199016158
#Sta/Elev= 30
       0 3197.96     5.8  3196.1    16.5 3194.15    54.5 3184.77    68.3 3180.94
    88.2 3172.37      91 3171.52   102.2 3169.86   113.6 3165.45   124.7 3163.55
  133.633158.269   136.6  3157.4   142.4 3157.47  147.673158.271   150.4 3159.31
   158.2 3163.57   161.7 3164.37   165.3 3164.61   178.7 3163.27   182.5 3163.75
   187.2 3167.16   192.8 3172.37   208.5 3184.12     214 3187.37     224 3192.26
   234.3 3198.36   247.3 3203.56   257.4 3205.24   263.9 3208.06273.2845 3211.07
#Mann= 4 ,-1,0
       0     .12       0      50      .1       0  133.63    .045       0
  147.67      .1       0
Bank Sta=133.63,147.67
XS Rating Curve= 0 ,0
Exp/Cntr(USF)=0,0
Exp/Cntr=0.3,0.1

Type RM Length L Ch R = 1 ,1827    ,136.4,130.8,123.7
XS GIS Cut Line= 4
2188172.44037713508538.5774911932188291.88651123508624.180553961
2188371.51726729508669.9682386972188423.27725873508703.811310024
#Sta/Elev= 30
       0 3196.44    14.4  3195.7    18.9 3194.34    47.5 3188.46    59.4 3185.17
    79.1 3176.93    96.3 3165.75    99.1 3163.59   104.9 3158.14   107.7 3156.51
   124.9 3157.23   142.4 3159.26   156.5 3159.35   161.1 3158.35   165.7 3154.95
   170.4 3152.88  182.143152.506   193.4 3151.55  199.673152.505   207.3 3156.43
   211.9 3156.88   221.1 3155.19   224.1 3156.29   230.3 3160.77   241.6 3164.62
   249.2 3168.23   264.7 3176.87     273 3180.06   292.2 3181.74300.6516 3183.42
#Mann= 4 ,-1,0
       0     .12       0  182.14    .045       0  199.67     .12       0
  206.95      .1       0
#XS Ineff= 2 , 0
                          212.54          3157.8
Permanent Ineff=
       F       F
Bank Sta=182.14,199.67
XS Rating Curve= 0 ,0
Exp/Cntr(USF)=0,0
Exp/Cntr=0.3,0.1

Type RM Length L Ch R = 1 ,1696    ,155.9,165.3,177.6
XS GIS Cut Line= 4
 2188136.6065369508697.8390033192188234.15421308508763.534377071
2188357.58188498508777.4697593822188425.26802763508821.266675216
#Sta/Elev= 30
       0 3177.03    13.1  3174.4    22.3 3173.63    47.7  3169.6    71.8 3169.51
   100.8 3161.86   105.6    3160   117.6 3153.81   120.9 3153.26   131.7 3153.28
   139.8  3149.5   143.8 3148.98   167.9 3147.88     180 3147.56  196.523148.102
   200.1 3149.41   208.2 3148.77   216.3 3148.88   224.3 3150.54   232.4 3153.17
   248.6 3153.89   255.1 3155.17   268.7 3161.89   278.3 3164.63     284 3166.86
   286.9 3168.52   292.8 3173.12   302.1 3177.85   311.6 3185.22 322.439 3191.07
#Mann= 6 ,-1,0
       0     .12       0      10      .1       0  127.61     .12       0
   167.9    .045       0  196.52     .12       0  207.61      .1       0
#XS Ineff= 2 , 0
                          201.76         3151.27
Permanent Ineff=
       F       F
Bank Sta=167.9,196.52
XS Rating Curve= 0 ,0
Exp/Cntr(USF)=0,0
Exp/Cntr=0.3,0.1

Type RM Length L Ch R = 1 ,1530    ,93.8,101.5,111.4
XS GIS Cut Line= 4
2188090.81885217 508787.423603892188190.35729725508853.118977641
2188283.92343562508950.6666538182188339.66496486509006.408183062
#Sta/Elev= 30
       0 3165.01    10.9 3163.29    22.5 3163.05      34 3163.89      60 3163.01
    65.8 3162.22    91.7 3154.78     112 3150.55   121.9  3147.5   124.9 3146.12
   130.4 3142.07   133.4 3140.95   150.8 3140.28   157.4 3142.67     163 3143.23
   180.3 3142.39   185.5 3141.11  189.443138.977   194.1 3138.17     208 3138.88
   216.8 3139.17   222.4 3140.67   225.3 3142.54   254.8  3168.9   263.6 3175.17
   270.5 3179.01   281.8  3183.9   301.6 3189.15   322.7 3201.35333.2611 3208.43
#Mann= 4 ,-1,0
       0     .12       0      60      .1       0  189.44    .045       0
     208      .1       0
#XS Ineff= 2 , 0
           169.8 3143.82
Permanent Ineff=
       F       F
Bank Sta=189.44,208
XS Rating Curve= 0 ,0
Exp/Cntr(USF)=0,0
Exp/Cntr=0.3,0.1

Type RM Length L Ch R = 1 ,1429    ,176.8,167.6,155.9
XS GIS Cut Line= 3
2188082.08071013508795.5630659052188152.41500363508924.328926315
2188176.22045681509096.377428879
#Sta/Elev= 30
       0  3164.2    29.2 3160.09    47.4 3156.31    56.5 3151.97    65.7 3148.36
    74.8 3141.72    79.5 3139.16    83.9 3138.47   105.9 3138.26   129.5  3134.5
   135.4 3135.38   143.1 3137.87   147.6 3138.68   150.8 3138.22   163.7 3134.08
   176.1 3132.27   183.9 3131.56     192 3132.26     196  3134.1   200.1 3137.54
   207.6 3145.15   216.2  3152.2   240.5 3176.75   252.6 3186.28   260.8 3187.96
   268.7 3190.65   276.8 3192.01     293 3196.83   305.1 3198.65   320.4 3197.07
#Mann= 4 ,-1,0
       0     .12       0      90      .1       0   176.1    .045       0
     192      .1       0
#XS Ineff= 2 , 0
          146.33  3138.7
Permanent Ineff=
       F       F
Bank Sta=176.1,192
XS Rating Curve= 0 ,0
Exp/Cntr(USF)=0,0
Exp/Cntr=0.3,0.1

Type RM Length L Ch R = 1 ,1261    ,206.8,203.8,203.2
XS GIS Cut Line= 4
2187901.69580652508902.8882001812187961.41887357 508952.65742272
2188076.88346986509046.2235610942188154.52345702509113.909703747
#Sta/Elev= 30
       0 3161.39    13.6 3159.05    31.8 3154.26    50.1 3150.51    91.3 3144.99
    94.3 3143.41     100 3138.85     107 3131.29   111.4 3128.27  114.833127.104
   119.9 3126.41   132.8 3126.99   142.6  3126.8   148.3 3128.03   171.1 3129.92
   179.6 3129.64   188.1 3130.97   193.8 3130.85   199.5 3129.39   205.2 3129.37
     210 3132.66   218.3 3141.59   220.3 3143.24   230.9 3149.56   250.6 3164.38
   267.6 3175.19   287.5 3184.68     296 3187.96   315.6 3191.49329.3598 3195.21
#Mann= 3 ,-1,0
       0      .1       0  114.83    .045       0   132.8      .1       0
#XS Ineff= 2 , 0
                           172.5         3131.64
Permanent Ineff=
       F       F
Bank Sta=114.83,132.8
XS Rating Curve= 0 ,0
Exp/Cntr(USF)=0,0
Exp/Cntr=0.3,0.1

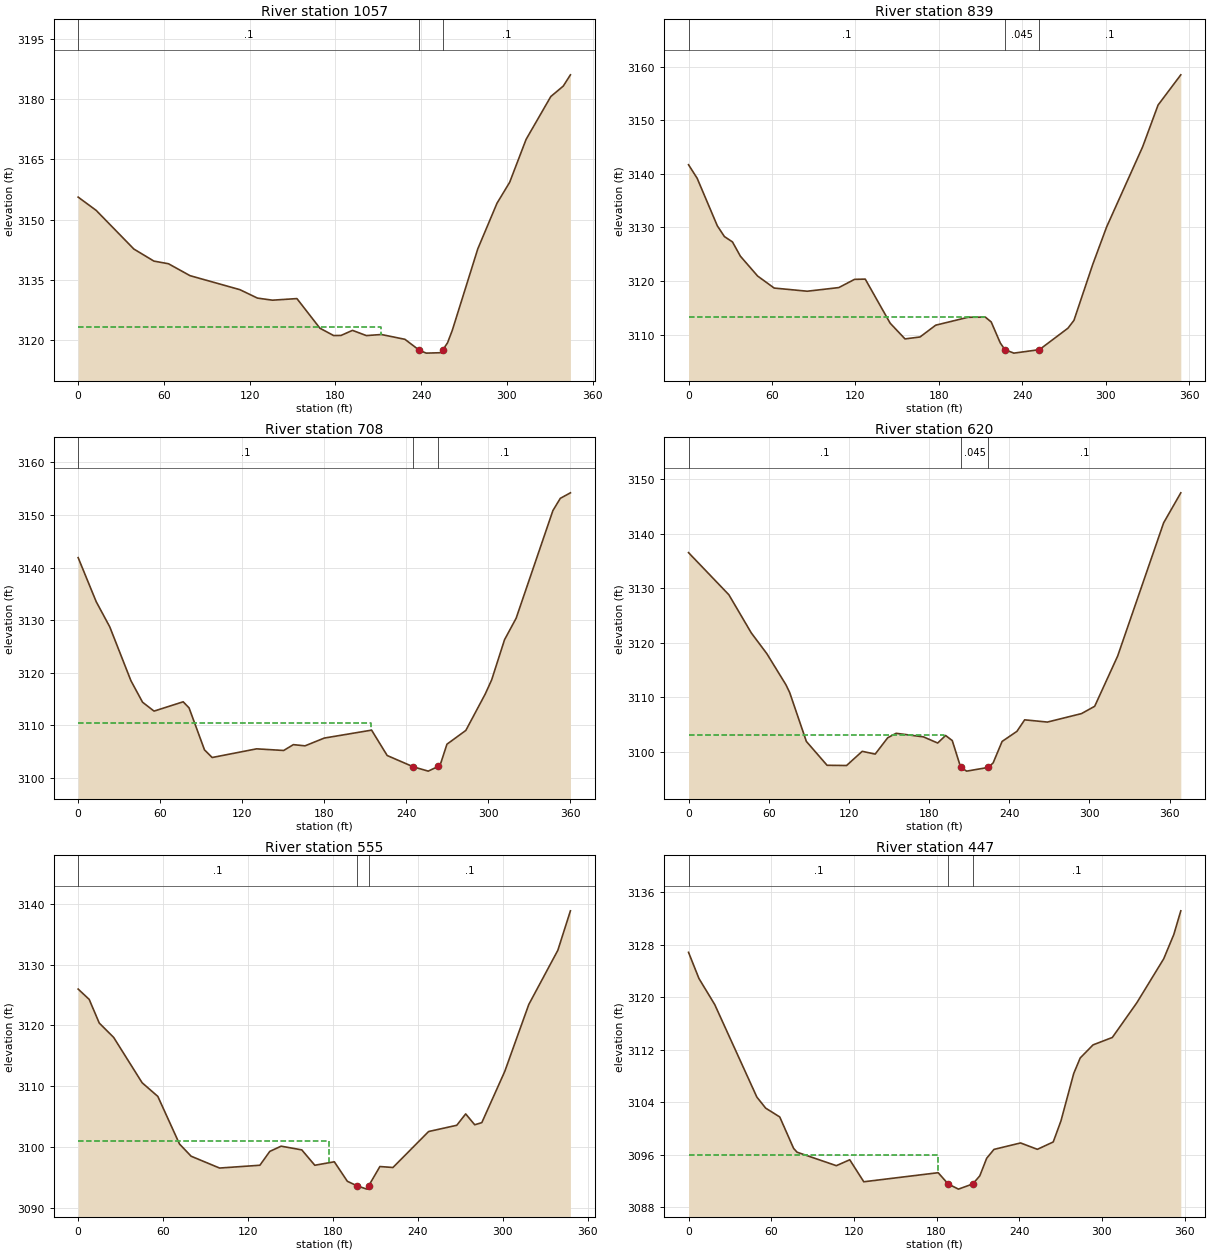
Type RM Length L Ch R = 1 ,1057    ,216.2,218.8,217.9
XS GIS Cut Line= 4
2187786.23121023 509016.362027572187909.65888212509111.918934846
2188015.16963391509189.5589220072188062.94808755509221.411224432
#Sta/Elev= 30
       0 3155.58    12.6 3152.28      39 3142.64      53 3139.64    63.2 3138.98
    78.3 3136.01   113.2 3132.52   125.5 3130.42     136  3129.9   153.1  3130.3
   169.2 3122.92   178.8 3121.09     184 3121.12     192 3122.38   201.7 3121.08
   212.2 3121.35   228.7 3120.15  238.763117.432   243.6 3116.71   253.6 3116.81
  255.023117.431   258.5 3119.27   261.8 3122.34   279.7  3142.7   293.1 3154.03
     302 3159.28   313.5 3169.97   330.8 3180.65   339.5 3183.24344.5152 3186.05
#Mann= 3 ,-1,0
       0      .1       0  238.76    .045       0  255.02      .1       0
#XS Ineff= 2 , 0
          211.77 3123.33
Permanent Ineff=
       F       F
Bank Sta=238.76,255.02
XS Rating Curve= 0 ,0
Exp/Cntr(USF)=0,0
Exp/Cntr=0.3,0.1

Type RM Length L Ch R = 1 ,839     ,127.8,130.5,134.9
XS GIS Cut Line= 4
2187656.83123163509131.8266238612187784.24044133509247.291220152
2187863.87119739509334.8850518212187913.64041993509374.700429853
#Sta/Elev= 30
       0  3141.7     6.2 3139.18    20.7 3130.32    25.8 3128.31    31.6 3127.31
    37.3 3124.65    49.7 3120.95    61.6 3118.71    85.4 3118.12   108.1  3118.8
   119.4 3120.33   127.1 3120.38     145 3112.17   155.7 3109.23   166.5 3109.59
   177.8 3111.79     201 3113.26   213.5 3113.29   217.7 3112.39   224.2 3108.49
  227.543107.225     234 3106.58  252.363107.226   272.9 3111.23   277.2 3112.68
   290.7  3123.1   300.7  3130.1   326.6 3145.03   337.7 3152.82354.0606 3158.46
#Mann= 3 ,-1,0
       0      .1       0  227.54    .045       0  252.36      .1       0
#XS Ineff= 2 , 0
          213.42 3113.36
Permanent Ineff=
       F       F
Bank Sta=227.54,252.36
XS Rating Curve= 0 ,0
Exp/Cntr(USF)=0,0
Exp/Cntr=0.3,0.1

Type RM Length L Ch R = 1 ,708     ,94.4,87.7,84.4
XS GIS Cut Line= 4
2187552.90391874509183.8514089862187697.84666031509328.794150554
2187739.10773273509401.7945094452187786.71666244509454.693320237
#Sta/Elev= 30
       0 3141.89    13.2 3133.51    23.1 3128.73    38.6 3118.47    47.1 3114.38
    55.5 3112.69    76.8 3114.46    81.1 3113.31    92.4 3105.31      98 3103.86
   130.5 3105.51   150.3  3105.2   157.4 3106.31   165.9 3106.08     180 3107.56
   214.6 3109.07     226 3104.24   245.1 3102.09     256 3101.27   263.3 3102.16
   265.2  3102.8   269.7 3106.39   283.5 3109.01   297.7 3115.94   302.4 3118.63
   311.8 3126.26   320.3 3130.36   347.2 3150.85   352.6 3153.17     360 3154.22
#Mann= 3 ,-1,0
       0      .1       0   245.1    .045       0   263.3      .1       0
#XS Ineff= 2 , 0
           214.3 3110.36
Permanent Ineff=
       F       F
Bank Sta=245.1,263.3
XS Rating Curve= 0 ,0
Exp/Cntr(USF)=0,0
Exp/Cntr=0.3,0.1

Type RM Length L Ch R = 1 ,620     ,67,65.4,64.7
XS GIS Cut Line= 4
2187471.68972378509259.2358335622187609.05277799 509370.71889205
2187678.72968954  509434.4234969 2187748.4066011509502.109639553
#Sta/Elev= 30
       0 3136.51    30.2 3128.79      47 3121.79    58.6    3118    72.9  3112.3
    75.7 3110.88    88.2 3101.91   103.7 3097.54   118.3  3097.5     130  3100.1
   139.7 3099.59   149.1 3102.59   155.4  3103.4   175.8 3102.75   186.5 3101.62
   192.4    3103   197.4 3102.07  203.733097.148   208.2 3096.47  224.35 3097.15
     228 3097.98   234.7 3101.91   245.8 3103.76   251.6 3105.87   268.6 3105.46
   294.1 3107.01     304 3108.35   321.2 3117.56   355.6 3141.97368.4598 3147.47
#Mann= 3 ,-1,0
       0      .1       0  203.73    .045       0  224.35      .1       0
#XS Ineff= 2 , 0
          191.42 3103.09
Permanent Ineff=
       F       F
Bank Sta=203.73,224.35
XS Rating Curve= 0 ,0
Exp/Cntr(USF)=0,0
Exp/Cntr=0.3,0.1

Type RM Length L Ch R = 1 ,555     ,107.5,108.5,108.9
XS GIS Cut Line= 4
2187421.71486798509328.7941505542187551.84594253509417.664152683
 2187630.1361825509462.0991537472187701.02058896509532.983560208
#Sta/Elev= 30
       0 3125.96     7.8 3124.26    14.9 3120.37    25.1    3118    45.2 3110.54
    56.3 3108.29    71.6 3100.46    79.8 3098.45    99.9  3096.5   128.4 3096.96
   135.4 3099.24   143.4  3100.1     158 3099.49   167.2 3096.96     181 3097.53
   190.2 3094.32   197.1 3093.57     204 3093.03   205.2 3093.55   213.2 3096.75
   222.4 3096.59   247.6 3102.51   267.5 3103.54   273.8 3105.41   280.2 3103.62
   285.2 3103.98   301.4  3112.4   318.4 3123.43   338.9 3132.34   347.8 3138.84
#Mann= 3 ,-1,0
       0      .1       0   197.1    .045       0   205.2      .1       0
#XS Ineff= 2 , 0
          177.21 3100.92
Permanent Ineff=
       F       F
Bank Sta=197.1,205.2
XS Rating Curve= 0 ,0
Exp/Cntr(USF)=0,0
Exp/Cntr=0.3,0.1

Type RM Length L Ch R = 1 ,447     ,54.1,43.1,38.6
XS GIS Cut Line= 4
 2187372.1512787509406.5527322782187483.63433719509494.146563947
2187583.17278227509565.8142444032187662.80353833509613.592698041
#Sta/Elev= 30
       0 3126.81     7.6 3122.81      19 3118.87    49.6 3104.77      56 3103.09
    66.2 3101.75    76.3 3096.95    78.8 3096.38   107.3 3094.33     117 3095.23
   127.2 3091.88   181.2 3093.26  188.443091.548   195.9 3090.76  206.283091.547
   211.4 3092.78   216.4 3095.46   221.7 3096.81     241 3097.79   253.2 3096.82
   264.7 3097.94   270.3 3101.14   279.6 3108.38   284.3 3110.73   293.6 3112.72
   307.6 3113.85   325.4 3119.14   344.9 3125.83   352.2 3129.51357.2978 3133.13
#Mann= 3 ,-1,0
       0      .1       0  188.44    .045       0  206.28      .1       0
#XS Ineff= 2 , 0
           181.3 3095.98
Permanent Ineff=
       F       F
Bank Sta=188.44,206.28
XS Rating Curve= 0 ,0
Exp/Cntr(USF)=0,0
Exp/Cntr=0.3,0.1

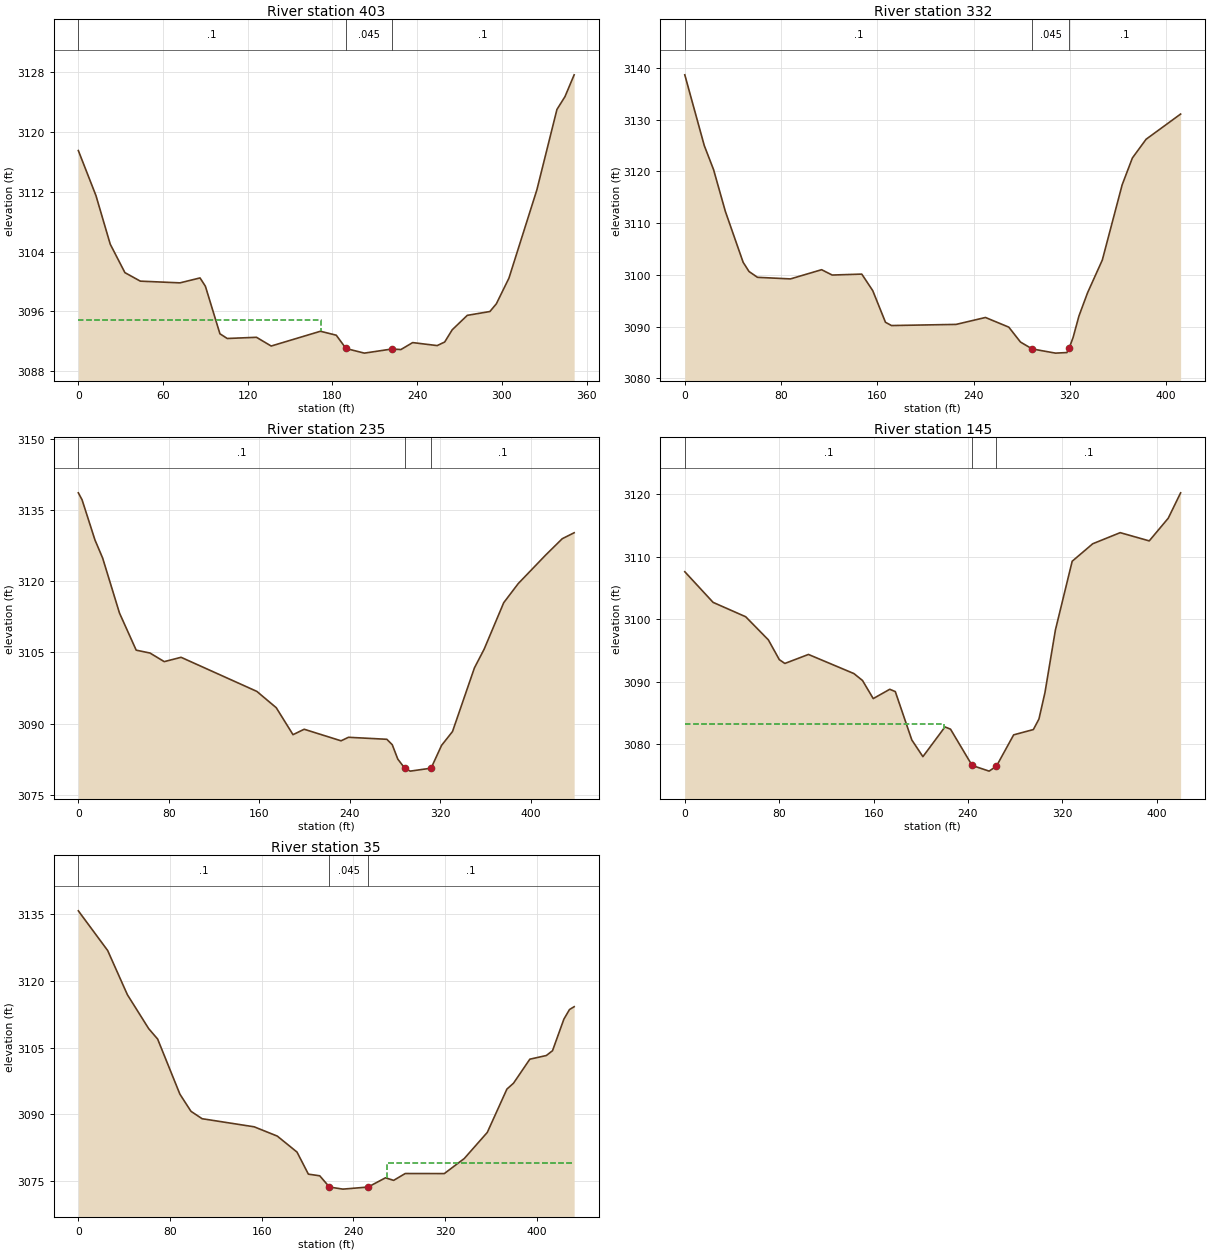
Type RM Length L Ch R = 1 ,403     ,61,71.7,80
XS GIS Cut Line= 4
2187338.72751415509441.2484112742187478.06860214509555.999895501
2187545.46233098509575.125142872 2187621.0525944509641.608145639
#Sta/Elev= 30
       0 3117.53    12.5 3111.49    22.6 3104.99      33 3101.18    43.9 3100.04
      72 3099.81    86.2 3100.47      90 3099.36   100.3 3092.99   105.5 3092.36
   126.2 3092.52   136.6 3091.35   171.5 3093.33   182.7  3092.8   189.6 3091.02
   202.6  3090.4     222 3090.95   228.5 3090.88   236.8 3091.81   254.2 3091.41
   259.5 3091.89   264.8 3093.52   275.5 3095.46   291.5 3095.97   296.1 3097.01
     305 3100.44   324.8 3112.27     339 3123.03   344.7 3124.75   351.2 3127.67
#Mann= 3 ,-1,0
       0      .1       0   189.6    .045       0     222      .1       0
#XS Ineff= 2 , 0
          172.06 3094.85
Permanent Ineff=
       F       F
Bank Sta=189.6,222
XS Rating Curve= 0 ,0
Exp/Cntr(USF)=0,0
Exp/Cntr=0.3,0.1

Type RM Length L Ch R = 1 ,332     ,102.2,96.3,95.9
XS GIS Cut Line= 4
2187280.82063193509457.8628421982187440.69259343 509573.06469681
2187565.29868108509658.8783232042187615.84643361509697.670784451
#Sta/Elev= 30
       0 3138.66    16.2 3124.98    23.9 3120.35    33.7 3112.28    48.5 3102.43
    53.4 3100.65    60.4 3099.53    87.8 3099.22   113.7    3101   122.5 3099.97
   147.1 3100.15   156.2 3096.96   166.8 3090.84   171.8 3090.21   225.5 3090.43
   249.9 3091.77   269.3  3089.9     279 3087.02   288.7 3085.69   308.1 3084.88
   317.6 3084.99   319.4 3085.83   322.7 3087.88   327.6 3092.06   334.8 3096.57
     347 3102.86   363.5  3117.4     372 3122.59   383.4 3126.21   412.1 3131.08
#Mann= 3 ,-1,0
       0      .1       0   288.7    .045       0   319.4      .1       0
Bank Sta=288.7,319.4
XS Rating Curve= 0 ,0
Exp/Cntr(USF)=0,0
Exp/Cntr=0.3,0.1

Type RM Length L Ch R = 1 ,235     ,91.2,90,89.4
XS GIS Cut Line= 4
2187230.80668669509537.9434797812187407.98511893509667.343458383
2187533.40355973509752.9465211512187589.14508897509790.771130281
#Sta/Elev= 30
       0 3138.59     3.3 3137.13    14.7 3128.68    21.5 3124.87    36.4  3113.3
    51.2 3105.48    63.4 3104.88      76 3103.07    90.9 3103.98   157.9 3096.81
   175.1 3093.37   189.9  3087.7   199.8 3088.84   232.4 3086.41     239 3087.15
   272.9 3086.73   277.7 3085.59   282.6 3082.56  288.753080.649   293.6 3080.03
  312.073080.651   321.3 3085.44     331 3088.36   350.4 3101.76     359  3105.7
   376.3 3115.47   389.1 3119.48   413.3 3125.47   428.1 3128.94438.6113 3130.19
#Mann= 3 ,-1,0
       0      .1       0  288.75    .045       0  312.07      .1       0
Bank Sta=288.75,312.07
XS Rating Curve= 0 ,0
Exp/Cntr(USF)=0,0
Exp/Cntr=0.3,0.1

Type RM Length L Ch R = 1 ,145     ,108.2,110.4,111.8
XS GIS Cut Line= 2
2187211.69513883509658.7911384352187570.86285811509876.857253712
#Sta/Elev= 30
       0 3107.61      24  3102.7    51.6  3100.4    70.8  3096.7    80.1 3093.53
    84.8 3092.92   104.8 3094.36   143.3  3091.3   150.6 3090.19   159.7 3087.29
   173.7 3088.78   178.4 3088.41   192.4 3080.66   201.8 3077.99   220.5 3082.75
   225.2 3082.39   243.5 3076.58   257.9 3075.67   264.1 3076.46   278.7 3081.48
   295.4 3082.33   300.1    3084   305.2 3088.22   314.1 3098.29   328.3 3109.29
   345.7 3112.09     369 3113.87   393.6 3112.55   409.7 3116.18   420.2 3120.25
#Mann= 3 ,-1,0
       0      .1       0   243.5    .045       0   264.1      .1       0
#XS Ineff= 2 , 0
          219.36 3083.22
Permanent Ineff=
       F       F
Bank Sta=243.5,264.1
XS Rating Curve= 0 ,0
Exp/Cntr(USF)=0,0
Exp/Cntr=0.3,0.1

Type RM Length L Ch R = 1 ,35      ,,,
XS GIS Cut Line= 4
2187171.08361964509744.9834455452187316.40974946509844.521890623
2187435.85588355509932.1157222922187523.44971522509995.820327142
#Sta/Elev= 30
       0 3135.81    25.6 3126.88    42.8 3116.94    61.4  3109.3    69.2 3106.96
    88.6 3094.57    98.3  3090.7     108 3089.04   153.4 3087.22   173.6 3085.13
   190.8 3081.53   200.7 3076.57   210.6  3076.2  219.08 3073.67   230.8  3073.2
  252.813073.671     268 3075.75   275.1 3075.17   285.2 3076.71   319.3  3076.7
   336.7 3080.08   356.8 3085.96   373.9  3095.7   379.7 3097.04   393.9 3102.43
   408.3 3103.26   413.7 3104.34   423.6 3111.43   428.5  3113.6432.5778 3114.24
#Mann= 3 ,-1,0
       0      .1       0  219.08    .045       0  252.81      .1       0
#XS Ineff= 2 , 0
                          269.53         3079.02
Permanent Ineff=
       F       F
Bank Sta=219.08,252.81
XS Rating Curve= 0 ,0
Exp/Cntr(USF)=0,0
Exp/Cntr=0.3,0.1
LCMann Table=0

Chan Stop Cuts=-1
Use User Specified Reach Order=0
Composite Channel Slope=5